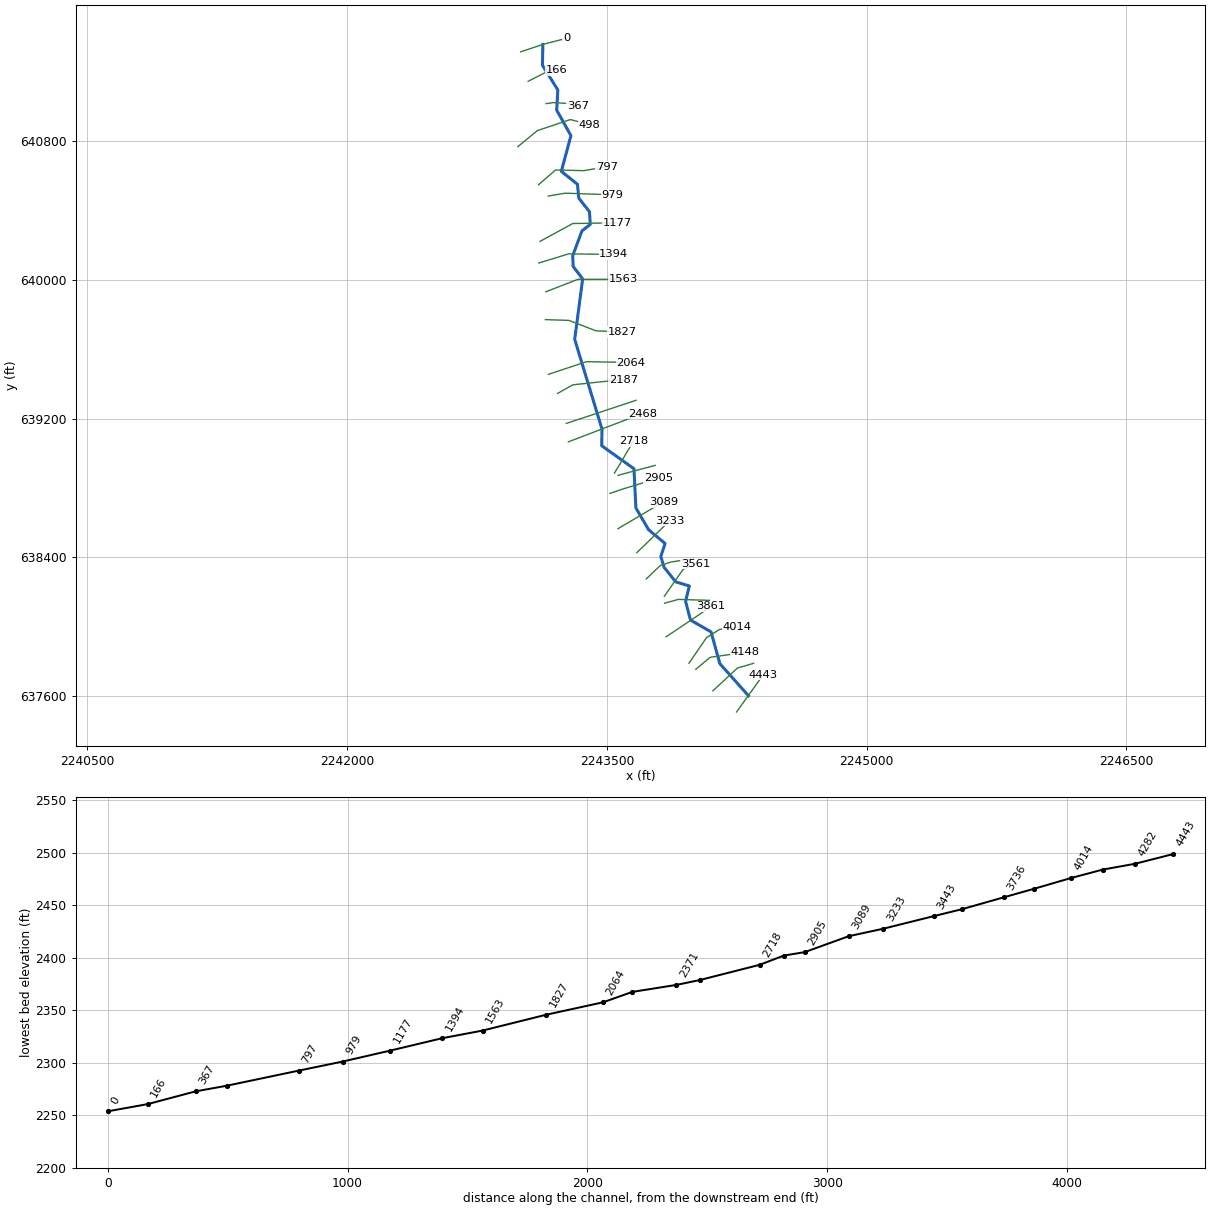
--- SUGARRN.prj (project) ---

Proj Title=SUGARRN
Current Plan=p01
Default Exp/Contr=0,0
English Units
Geom File=g01
Flow File=f01
Plan File=p01
BEGIN DESCRIPTION:
----------MODEL BY WOOD PLC 2022----------
AFH study:Sugar Run
Randolph County, WV
HEC-RAS Version: RAS 6.2
Vertical Datum: NAVD88
Projection: NAD 1983 StatePlane West Virginia S FIPS 4702 (US Feet)
Terrain: 1-meter LIDAR (FEMA Region III 3DEP collected 2016-2018)
Land Use: 2019 NLCD
Hydrologic Method:
WV SIR2010-5033 regression equations
Additional Model Notes:
Dominant flow path issue at confluence with SPICERN, but because of the coincident peak situation with SPICERN, as well as NHD lines naming the reach DS of the confluence as SPICERN, SPICERN was not split up.
Shared XS with SPICERN and KWSEL tie-in used
END DESCRIPTION:
DSS Export Rating Curves= 0
DSS Export Rating Curve Sorted= 0
DSS Export Volume Flow Curves= 0
DXF OffsetX= 0
DXF OffsetY= 0
DXF ScaleX= 0
DXF ScaleY= 0

--- SUGARRN.p01 (plan) ---

Plan Title=Floodplain
Program Version=6.20
Short Identifier=Floodplain
Geom File=g01
Flow File=f01
Subcritical Flow
K Sum by GR= 0
Std Step Tol= 0.01
Critical Tol= 0.01
Num of Std Step Trials= 20
Max Error Tol= 0.3
Flow Tol Ratio= 0.001
Split Flow NTrial= 30
Split Flow Tol= 0.02
Split Flow Ratio= 0.02
Log Output Level= 0
Friction Slope Method= 1
Unsteady Friction Slope Method= 2
Unsteady Bridges Friction Slope Method= 1
Parabolic Critical Depth
Global Vel Dist= 0 , 0 , 0
Global Log Level= 0
CheckData=True
Encroach Param=-1 ,0,0, 0
Mapping Interval=1HOUR
Computation Time Step Use Courant=        0
Computation Time Step Use Time Series=    0
Computation Time Step Count To Double=0
Computation Time Step Max Doubling=0
Computation Time Step Max Halving=0
Computation Time Step Residence Courant=0
Run HTab= 0
Run UNet= 0
Run Sediment= 0
Run PostProcess= 0
Run WQNet= 0
Run RASMapper=-1
UNET Theta= 0
UNET Theta Warmup= 0
UNET ZTol= 0
UNET ZSATol= 0
UNET MxIter= 0
UNET Max Iter WO Improvement= 0
UNET MaxInSteps= 0
UNET DtIC= 0
UNET DtMin= 0
UNET MaxCRTS= 0
UNET WFStab= 0
UNET SFStab= 0
UNET WFX= 1
UNET SFX= 1
UNET Gravity=32.174
UNET 1D Methodology=Finite Difference
UNET DSS MLevel= 1
UNET Pardiso=0
UNET DZMax Abort= 0
UNET Use Existing IB Tables= 0
UNET Froude Reduction=False
UNET Froude Limit= 0
UNET Froude Power= 0
UNET D1 Cores= 0
UNET WindReference=Eulerian
UNET WindDragFormulation=Hsu (1988)
UNET D2 Coriolis=0
UNET D2 Cores= 0
UNET D2 Theta= 1
UNET D2 Theta Warmup= 1
UNET D2 Z Tol= 0.01
UNET D2 Volume Tol= 0.01
UNET D2 Max Iterations= 20
UNET D2 Equation= 0
UNET D2 RampUpFraction=0.1
UNET D2 TimeSlices= 1
UNET D2 Turbulence Formulation=Non-Conservative (original)
UNET D2 Eddy Viscosity=0.3
UNET D2 Transverse Eddy Viscosity=0.1
UNET D2 Smagorinsky Mixing=0
UNET D2 BCVolumeCheck=0
UNET D2 Cores=0
UNET D2 SolverType=PARDISO (Direct)
UNET D2 Minimum Iterations= 2147483647
UNET D2 Maximum Iterations= 2147483647
UNET D2 Restart Number= 10
UNET D2 Relaxation Coeff=1.3
UNET D2 SOR Precondition Iterations= 10
UNET D2 ILUT Maximum Fill= 8
UNET D2 ILUT Tolerance=1E-08
UNET D1D2 MaxIter= 0
UNET D1D2 ZTol=0.01
UNET D1D2 QTol=0.1
UNET D1D2 MinQTol=1
Write IC File= 0
Write IC File at Fixed DateTime=0
Write IC File at Sim End=0
Echo Input=False
Echo Parameters=False
Echo Output=False
Write Detailed= 0
HDF Write Warmup=0
HDF Write Time Slices=0
HDF Flush=0
HDF Compression= 1
HDF Chunk Size= 1
HDF Spatial Parts= 1
HDF Use Max Rows=0
HDF Fixed Rows= 1
Calibration Method= 0
Calibration Iterations= 20
Calibration Max Change=0.05
Calibration Tolerance=0.2
Calibration Maximum=1.5
Calibration Minimum=0.5
Calibration Optimization Method= 1
WQ AD Non Conservative
WQ ULTIMATE=-1
WQ Max Comp Step=1HOUR
WQ Output Interval=15MIN
WQ Output Selected Increments= 0
WQ Output face flow=0
WQ Output face velocity=0
WQ Output face area=0
WQ Output face dispersion=0
WQ Output cell volume=0
WQ Output cell surface area=0
WQ Output cell continuity=0
WQ Output cumulative cell continuity=0
WQ Output face conc=0
WQ Output face dconc_dx=0
WQ Output face courant=0
WQ Output face peclet=0
WQ Output face adv mass=0
WQ Output face disp mass=0
WQ Output cell mass=0
WQ Output cell source sink temp=0
WQ Output nsm pathways=0
WQ Output nsm derived pathways=0
WQ Create Restart=0
WQ Fixed Restart=0
WQ System Summary=0
WQ Write To DSS=0
Sorting and Armoring Iterations= 10
XS Update Threshold= 0.02
Bed Roughness Predictor= 0
Hydraulics Update Threshold= 0.02
Energy Slope Method= 1
Volume Change Method= 1
Sediment Retention Method= 0
Sediment TS Multiplier= 1
Warm Up Method= 0
XS Weighting Method= 0
Number of US Weighted Cross Sections= 1
Number of DS Weighted Cross Sections= 1
Upstream XS Weight=0
Main XS Weight=1
Downstream XS Weight=0
Number of DS XS's Weighted with US Boundary= 1
Upstream Boundary Weight= 1
Weight of XSs Associated with US Boundary= 0
Number of US XS's Weighted with DS Boundary= 1
Downstream Boundary Weight= 0.5
Weight of XSs Associated with DS Boundary= 0.5
Percentile Method= 0
Sediment Output Level= 3
Mass or Volume Output= 0
Output Increment Type= 1
Profile and TS Output Increment= 1
Transport Output Increment 1
XS Output Flag= 0
XS Output Increment= 10
Read HDF5 Sediment Hotstart= 0
Sediment Hotstart Type= 0
Write Gradation File= 0
Read Gradation Hotstart= 0
Write HDF5 File= 1
Write Binary Output= 1
Write DSS Sediment File= 0
DSS Sediment Output Type= 1
SV Curve= 0
Specific Gage Flag= 0
Subcell Erosion Methods= 0
Subcell Deposition Methods= 0
Advection Scheme= 1
Matrix Solver= 0
Implicit Weighting Factor= 1
Maximum Outer Loop Convergence Iterations= 5
Convergence Maximum Absolute= 0.001
Convergence RMSE= 0.0001
Grain Fractions Max Abs Error= 0.001
Max Subgrid Regions= 1
Max Subgrid Length Scale= 3.402823E+38
Initial Layer Thickness= 3.402823E+38
Min Layer Thickness= 3.402823E+38
Max Layer Thickness= 3.402823E+38
Number of Layers= 5

--- SUGARRN.f01 (steady flow) ---

Flow Title=Flow
Program Version=6.20
Number of Profiles= 1
Profile Names=P100yr
River Rch & RM=SUGARRN,Main            ,4443
     352
River Rch & RM=SUGARRN,Main            ,0
     590
Boundary for River Rch & Prof#=SUGARRN,Main            , 1
Up Type= 0
Dn Type= 1
Dn Known WS=2257.2
DSS Import GetInterval= 0
DSS Import GetPeak= 0
DSS Import FillOption= 0

--- SUGARRN.g01 (geometry) ---

Geom Title=Geometry
Program Version=6.20

River Reach=SUGARRN         ,Main
Reach XY= 30
2244317.64644921637600.2472753972244152.31100002637785.562000021
2244101.53000002637969.1560000032243982.71500005638037.230000019
2243954.39399999638145.3710000372243976.09600003638233.913000003
     2243897.537638257.7849999962243830.26199999638341.552000016
2243811.59900001638404.4860000012243835.90500003638479.572999999
2243740.85300002638558.566000015     2243667.455638684.262000009
2243656.21700001638910.9960000222243470.01900002      639043.375
2243471.74766679639139.1703152812243314.03500001639657.647000015
2243359.93478963640006.6225054562243304.82800002640078.618000016
2243302.74500002640141.1180000162243356.04600002640284.020999998
2243403.90399998640320.9500000182243399.27300003640394.243000016
2243337.38661034640472.9410557452243329.91977714640552.700944737
2243236.82300001640627.2720000152243292.23200001640833.063999996
     2243210.036 640980.701000022243216.50700001 641097.10800001
2243127.74500002641239.0350000112243130.04460749641359.776593611

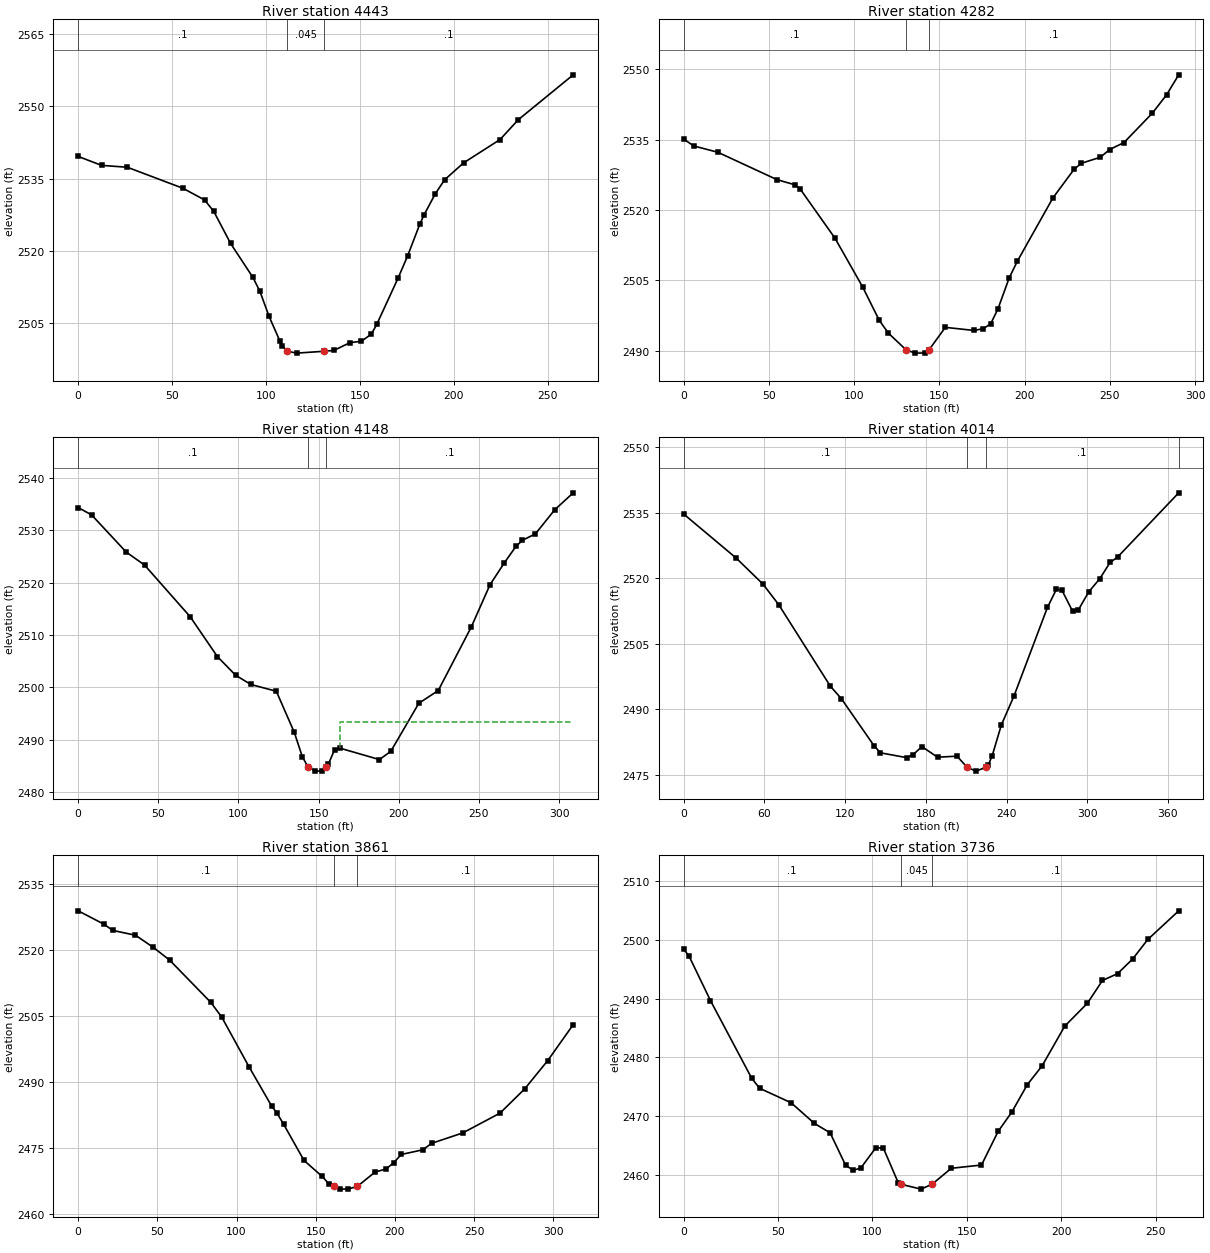
Type RM Length L Ch R = 1 ,4443    ,161.7,160.9,157.3
XS GIS Cut Line= 2
2244248.91048694 637506.501391662244402.44846949 637720.93991478
#Sta/Elev= 30
       0 2539.63    12.5 2537.77    26.2 2537.38    55.9    2533    67.3  2530.6
    72.2 2528.24    81.2 2521.56    93.1  2514.5    96.8 2511.62   101.7 2506.41
   107.5 2501.25   108.7 2500.36  111.27  2499.2   116.4 2498.79   131.2 2499.18
   136.2 2499.35   144.7 2500.95   150.9 2501.27   156.2 2502.74   159.1  2504.8
   170.5 2514.45   175.5 2518.99     182 2525.59   184.3 2527.53   190.2 2531.86
   195.2 2534.78   205.3 2538.29   224.7 2543.13   234.5 2547.27   263.7 2556.57
#Mann= 3 ,-1,0
       0      .1       0  111.27    .045       0   131.2      .1       0
Bank Sta=111.27,131.2
XS Rating Curve= 0 ,0
Exp/Cntr(USF)=0,0
Exp/Cntr=0.3,0.1

Type RM Length L Ch R = 1 ,4282    ,137.8,133.1,130.9
XS GIS Cut Line= 3
2244112.02871253637628.8717117952244254.14448261637760.497639376
2244347.04596297637787.326104029
#Sta/Elev= 30
       0 2535.12       6 2533.66    20.1 2532.31    54.7 2526.48    65.4 2525.36
    68.3  2524.5    88.8 2513.96     105 2503.57   114.7 2496.48   120.1 2493.72
   130.5 2490.15   135.8 2489.46   141.8  2489.5  143.91 2490.15   153.5 2494.96
   170.2  2494.3   175.8 2494.67   180.1 2495.74   184.3 2498.84     191 2505.55
   195.8 2509.12   216.6 2522.58   229.1 2528.72   233.3 2529.97   244.4 2531.25
   249.9  2532.9   258.3 2534.39   274.9 2540.65   283.3 2544.59   290.4 2548.84
#Mann= 3 ,-1,0
       0      .1       0   130.5    .045       0  143.91      .1       0
Bank Sta=130.5,143.91
XS Rating Curve= 0 ,0
Exp/Cntr(USF)=0,0
Exp/Cntr=0.3,0.1

Type RM Length L Ch R = 1 ,4148    ,131.4,134.4,136.8
XS GIS Cut Line= 3
2244013.72801632 637753.33587743 2244096.3605773637822.361327547
2244295.52681982637850.411762318
#Sta/Elev= 30
       0 2534.38     8.4 2532.96      30 2525.85    41.4 2523.38    69.8 2513.52
    86.8 2505.89    98.2 2502.31   107.7 2500.54   123.6 2499.25   134.8 2491.39
   139.8 2486.74143.33552484.784   147.9 2483.97   151.9    2484  154.41 2484.78
     156 2485.27     160 2488.09   163.1 2488.38   187.9 2486.18     195 2487.75
   212.5 2496.95   224.6 2499.38   245.2 2511.52   256.9 2519.62   265.8 2523.79
   273.1 2526.96   277.1 2528.11   285.2 2529.34   297.3 2533.96   308.8 2537.19
#Mann= 3 ,-1,0
       0      .1       0143.3355    .045       0  154.41      .1       0
#XS Ineff= 2 , 0
                          163.58         2493.32
Permanent Ineff=
       F       F
Bank Sta=143.3355,154.41
XS Rating Curve= 0 ,0
Exp/Cntr(USF)=0,0
Exp/Cntr=0.3,0.1

Type RM Length L Ch R = 1 ,4014    ,153.1,152.7,153.1
XS GIS Cut Line= 4
2243974.35235838637788.6875032432244076.37827757637936.818829415
2244151.39731954637983.434133522 2244250.4306002637995.955392609
#Sta/Elev= 30
       0 2534.67    39.1 2524.57    58.9 2518.65    70.7 2513.91     109 2495.29
   117.2 2492.43   141.4  2481.7   146.3 2480.03   165.7 2478.93   170.6 2479.62
   177.1 2481.45   188.7 2479.03   203.2 2479.26 210.7822476.694   217.3 2475.84
  224.56  2476.7   226.5 2477.27   229.4 2479.41   236.1 2486.36   245.6 2493.07
   270.4 2513.29     277  2517.4   281.1 2517.29   289.1 2512.44   293.2 2512.64
   301.2 2516.89   309.3 2519.85     317  2523.6   322.5  2524.8     368 2539.52
#Mann= 4 ,-1,0
       0      .1       0 210.782    .045       0  224.56      .1       0
  368.01     .06       0
Bank Sta=210.782,224.56
XS Rating Curve= 0 ,0
Exp/Cntr(USF)=0,0
Exp/Cntr=0.3,0.1

Type RM Length L Ch R = 1 ,3861    ,130.8,125.6,121.3
XS GIS Cut Line= 3
 2243842.5162698637941.0837174062244021.62358678638060.706487507
2244101.37210018638116.268976352
#Sta/Elev= 30
       0 2528.81    16.4 2525.75    21.8 2524.37    36.2 2523.27    47.4 2520.53
    57.8 2517.61    83.8 2508.02    90.7 2504.67   107.8 2493.48   122.2 2484.49
   125.3 2483.05   129.8 2480.35   142.6 2472.18   154.1 2468.54   158.6 2466.75
   161.72466.274   165.5  2465.7   170.3 2465.67  176.25 2466.28   187.4 2469.52
   194.5 2470.27   199.2 2471.64     204 2473.53   217.6 2474.59   223.2 2476.06
   242.9 2478.43   266.4 2482.92   281.9 2488.39   296.5 2494.83   312.6 2502.99
#Mann= 3 ,-1,0
       0      .1       0   161.7    .045       0  176.25      .1       0
Bank Sta=161.7,176.25
XS Rating Curve= 0 ,0
Exp/Cntr(USF)=0,0
Exp/Cntr=0.3,0.1

Type RM Length L Ch R = 1 ,3736    ,163.9,174.5,180.1
XS GIS Cut Line= 3
2243833.34524859638134.4901452572243912.44923712638156.410527621
2244092.61667508638151.056364216
#Sta/Elev= 30
       0 2498.44     2.9 2497.21    14.2 2489.67    36.1 2476.41    40.3 2474.73
    56.9 2472.28    69.3 2468.75    77.6 2467.16    85.8 2461.63    89.8 2460.79
    93.8 2461.14   101.8 2464.61   105.8 2464.56   113.8 2458.58     1152458.406
   125.8 2457.57   131.72458.422   141.8 2461.12   157.8 2461.67   166.6 2467.39
   173.9 2470.71   182.1 2475.37   189.9 2478.55   201.9 2485.31   213.9 2489.21
   221.9 2493.09   229.9 2494.26   237.9 2496.75   245.9 2500.07   262.3 2504.95
#Mann= 3 ,-1,0
       0      .1       0     115    .045       0   131.7      .1       0
Bank Sta=115,131.7
XS Rating Curve= 0 ,0
Exp/Cntr(USF)=0,0
Exp/Cntr=0.3,0.1

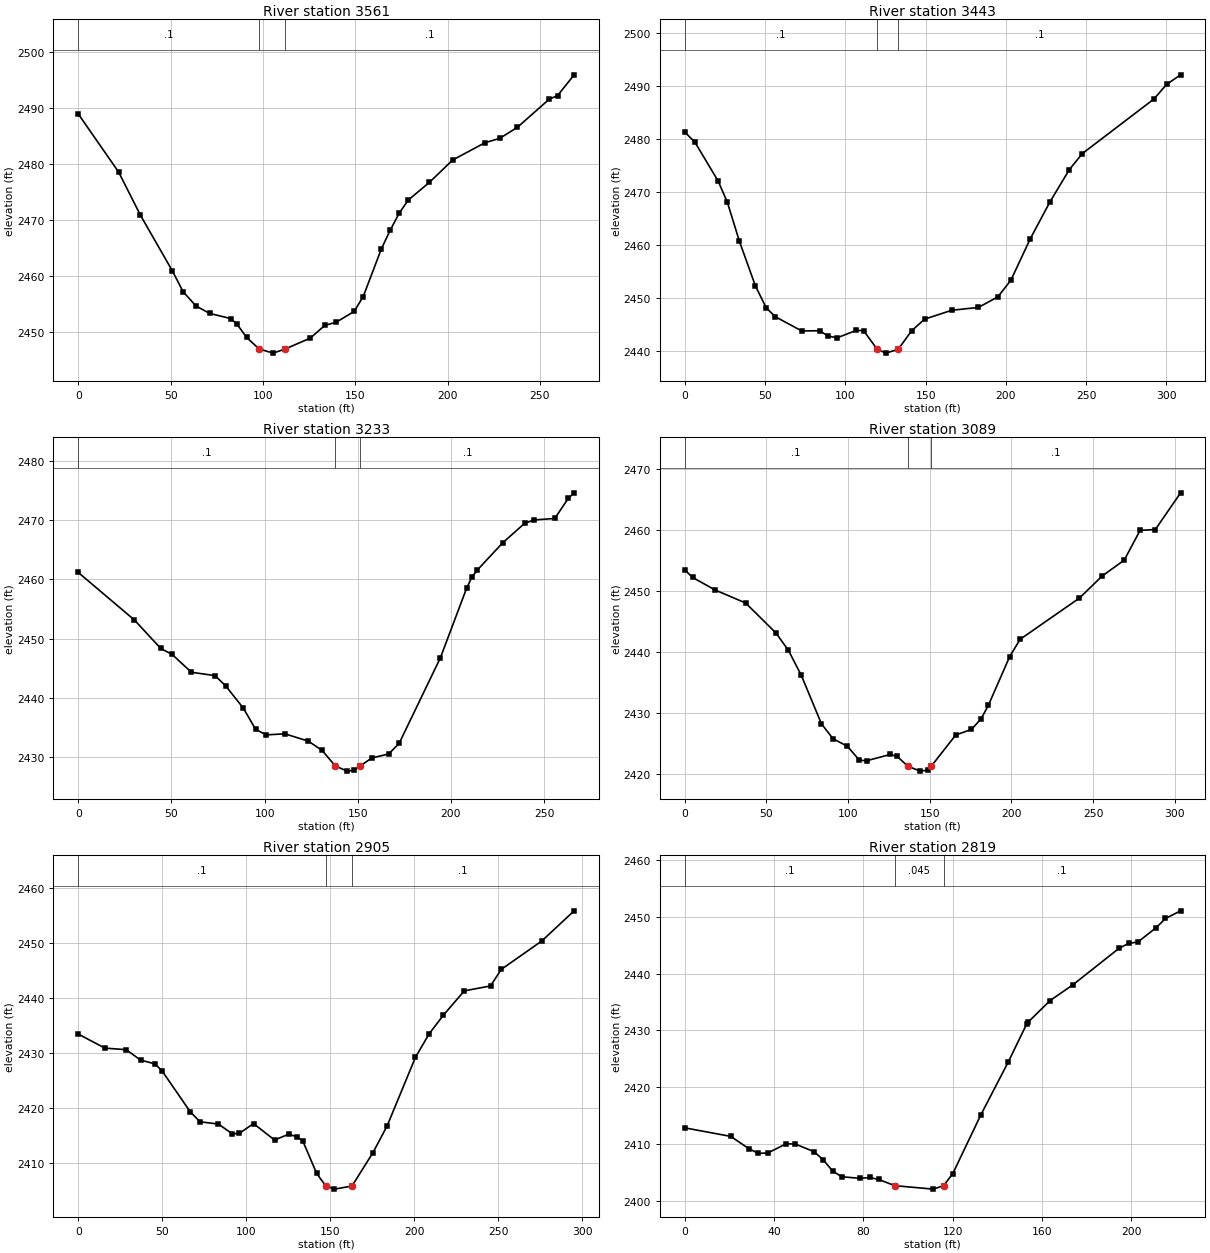
Type RM Length L Ch R = 1 ,3561    ,123,118.4,114.4
XS GIS Cut Line= 3
 2243831.6378043 638174.744763452243940.58386086638330.497273938
2244012.40755741638361.970579166
#Sta/Elev= 30
       0 2488.92    21.9 2478.53    33.7 2470.84      51  2460.9    56.8  2457.2
    63.7 2454.68    71.1 2453.34    82.6 2452.41      86  2451.4    91.2 2449.04
    97.9    2447   105.5 2446.25     112 2446.98   125.6 2448.92   133.5 2451.19
   139.7 2451.77   149.4 2453.68   154.3 2456.34   164.1 2464.82   168.9 2468.16
   173.8 2471.22   178.7 2473.55   190.1 2476.69   202.7 2480.68   220.2 2483.77
   228.2 2484.55   237.7  2486.5   255.1 2491.56   259.5 2492.17   268.5 2495.88
#Mann= 3 ,-1,0
       0      .1       0    97.9    .045       0     112      .1       0
Bank Sta=97.9,112
XS Rating Curve= 0 ,0
Exp/Cntr(USF)=0,0
Exp/Cntr=0.3,0.1

Type RM Length L Ch R = 1 ,3443    ,206.5,210,212.3
XS GIS Cut Line= 4
2243727.57369756638274.7508178862243807.30960933638351.212705443
2243867.23754859 638371.712385832244000.66209508638392.430091197
#Sta/Elev= 30
       0 2481.31     6.4 2479.36    20.8 2472.07    26.6 2468.02    34.1 2460.67
      44 2452.31    50.7 2448.17    56.3 2446.49    72.9 2443.78      84 2443.82
    89.5  2442.8      95  2442.5   106.8 2443.88   111.4 2443.85   119.8 2440.34
   125.3  2439.6  132.98 2440.33   141.3 2443.81   149.4 2446.01   166.3 2447.68
   182.9 2448.22     195 2450.21   203.1 2453.34   215.2 2461.17   227.4  2468.1
   239.5  2474.2   247.6 2477.23   292.1  2487.5   300.2 2490.31   308.8 2492.08
#Mann= 3 ,-1,0
       0      .1       0   119.8    .045       0  132.98      .1       0
Bank Sta=119.8,132.98
XS Rating Curve= 0 ,0
Exp/Cntr(USF)=0,0
Exp/Cntr=0.3,0.1

Type RM Length L Ch R = 1 ,3233    ,145.2,143.7,141.9
XS GIS Cut Line= 2
2243672.57906028638426.0938730862243863.59781277638611.302169234
#Sta/Elev= 30
       0 2461.19    30.2 2453.14    44.3 2448.34    50.4 2447.34    60.7 2444.33
    73.4 2443.76    79.1 2442.03    88.6 2438.27    95.2 2434.68   100.9 2433.75
   110.9 2433.93   123.5 2432.69   130.9 2431.12   137.9 2428.52   144.3 2427.63
   148.1 2427.79   151.42428.523   157.5 2429.85   166.6 2430.53   172.2 2432.32
   194.3 2446.75   208.4 2458.52   211.2 2460.37   214.1 2461.58   227.9 2466.23
   239.5 2469.47   244.6 2470.05   255.7  2470.3     263 2473.72   266.1 2474.63
#Mann= 3 ,-1,0
       0      .1       0   137.9    .045       0   151.4      .1       0
Bank Sta=137.9,151.4
XS Rating Curve= 0 ,0
Exp/Cntr(USF)=0,0
Exp/Cntr=0.3,0.1

Type RM Length L Ch R = 1 ,3089    ,186.2,184,182.9
XS GIS Cut Line= 2
2243564.08172188638564.9163242952243825.55225762638719.054819127
#Sta/Elev= 30
       0 2453.49     4.8 2452.24    18.7 2450.17    37.3 2448.05    55.8 2443.16
    63.5 2440.29    71.4 2436.19    83.7 2428.26    90.8 2425.82    99.6 2424.59
   106.9 2422.31   111.3 2422.22   125.9 2423.25   130.1 2422.92   136.5 2421.33
   144.1 2420.52   148.7 2420.68   150.92421.329   165.9 2426.44   175.5 2427.35
   181.4 2429.09   185.8 2431.27   198.9 2439.28   205.3 2442.11   241.6 2448.86
   255.5 2452.47     269 2455.07   278.7 2459.95     288 2460.08   303.5 2466.09
#Mann= 3 ,-1,0
       0      .1       0   136.5    .045       0   150.9      .1       0
Bank Sta=136.5,150.9
XS Rating Curve= 0 ,0
Exp/Cntr(USF)=0,0
Exp/Cntr=0.3,0.1

Type RM Length L Ch R = 1 ,2905    ,85.9,86.5,86.9
XS GIS Cut Line= 3
2243517.12434605638768.0478571322243578.99494607638789.568065835
2243798.68040991 638856.81871803
#Sta/Elev= 30
       0 2433.48    15.9 2430.92    28.6 2430.64    37.1 2428.75    45.6 2428.07
    49.8 2426.84    66.7 2419.36    72.5 2417.54    83.5 2417.12    91.8 2415.34
      96 2415.45   104.4 2417.21   116.9 2414.22   125.3 2415.27   130.2 2414.82
   133.7 2414.07     142 2408.14  147.43 2405.87   152.6  2405.3     163 2405.86
   175.5 2411.93   183.9 2416.76   200.8 2429.25     209 2433.54   217.3 2436.86
   229.9 2441.33   245.5 2442.22   251.9 2445.23   275.9 2450.36   295.3 2455.87
#Mann= 3 ,-1,0
       0      .1       0  147.43    .045       0     163      .1       0
Bank Sta=147.43,163
XS Rating Curve= 0 ,0
Exp/Cntr(USF)=0,0
Exp/Cntr=0.3,0.1

Type RM Length L Ch R = 1 ,2819    ,95.6,100.5,110.3
XS GIS Cut Line= 3
2243564.32195185 638872.476469962243655.18296302638897.316170855
2243778.72779116638929.999987823
#Sta/Elev= 30
       0 2412.86    20.6 2411.36    28.9 2409.15      33 2408.37    37.2 2408.43
    45.5 2410.07    49.6    2410    57.9 2408.66      62 2407.25    66.2 2405.26
    70.3 2404.25    78.5 2403.97    82.8 2404.12    86.9 2403.77   94.01 2402.68
   111.3 2402.07   115.9 2402.68     120 2404.79   132.5 2415.09   144.9  2424.5
   153.1 2431.15   153.8  2431.5   163.6 2435.28   173.8 2438.05   194.5 2444.49
   198.7 2445.33   202.9 2445.59   211.1 2448.12   215.2 2449.72     222 2451.07
#Mann= 3 ,-1,0
       0      .1       0   94.01    .045       0   115.9      .1       0
Bank Sta=94.01,115.9
XS Rating Curve= 0 ,0
Exp/Cntr(USF)=0,0
Exp/Cntr=0.3,0.1

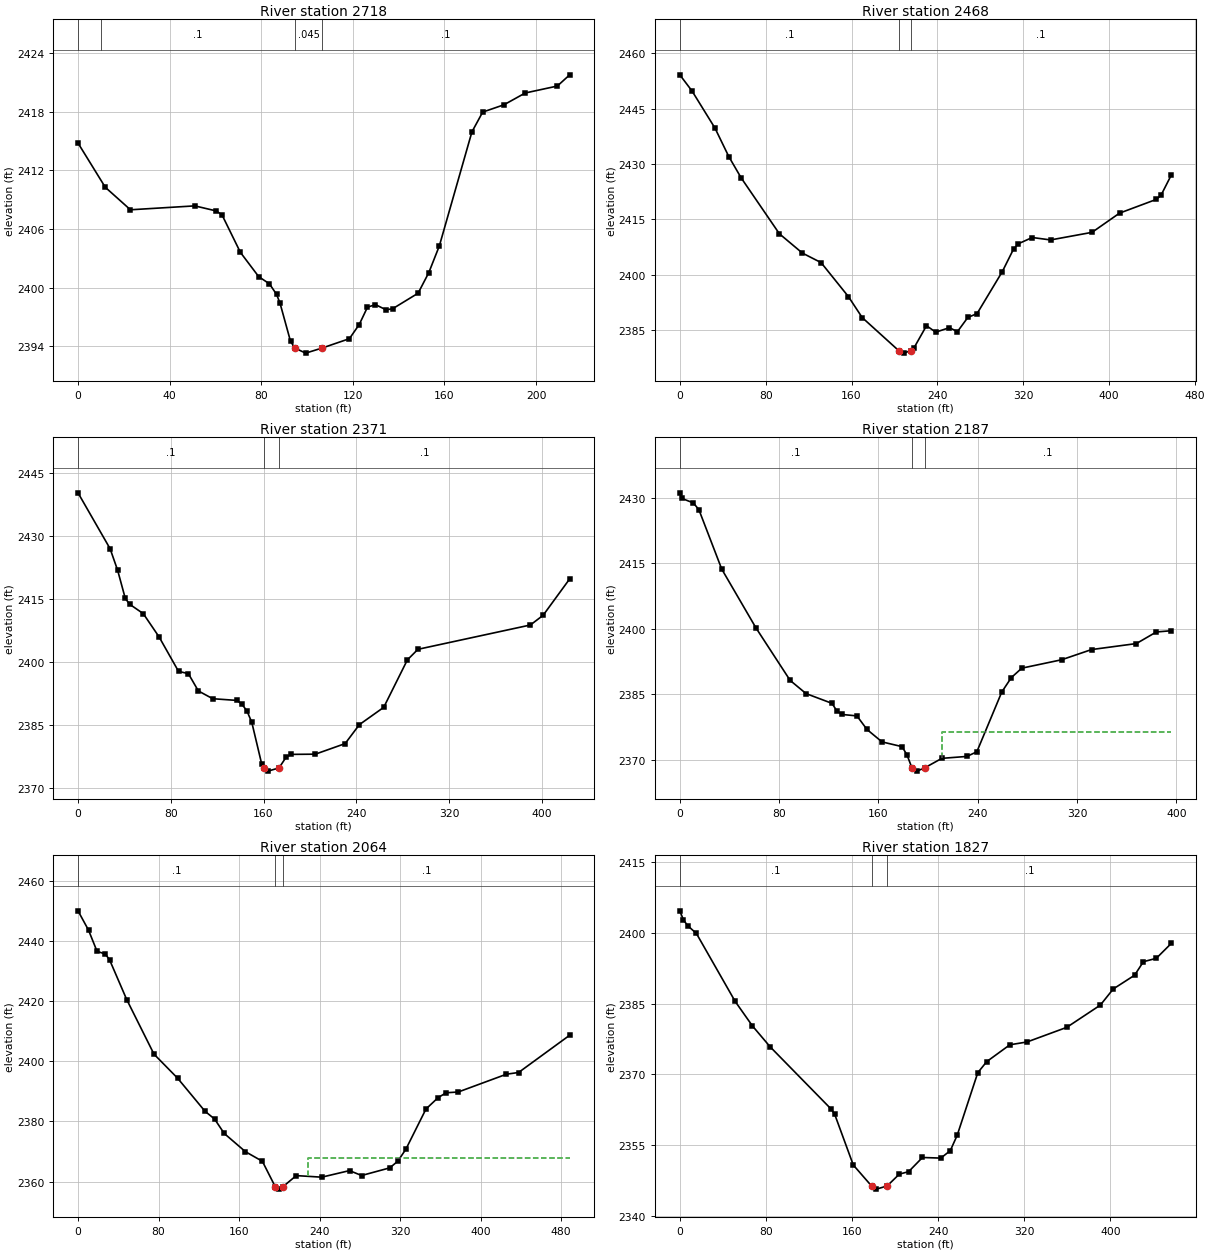
Type RM Length L Ch R = 1 ,2718    ,253.7,250.4,245.7
XS GIS Cut Line= 5
 2243543.3380022 638885.660572372243575.36814283638937.954679517
2243616.54975221639008.5517241662243637.46739507639042.542893812
2243653.68814605639069.760146929
#Sta/Elev= 30
       0 2414.81    11.9 2410.28    22.9 2407.97      51 2408.37    60.4 2407.85
    62.9 2407.44    70.9 2403.61    78.9 2401.12    83.6 2400.38    86.7  2399.3
    88.2 2398.41    92.8 2394.49    94.7  2393.8    99.4 2393.28   106.7 2393.81
   118.5 2394.76   122.8 2396.21   126.4 2397.99   129.9 2398.25   134.5 2397.72
   137.4 2397.83   148.5 2399.42   153.2 2401.54   157.8 2404.28     172 2415.95
   176.7 2417.98     186 2418.73   195.3 2419.94   209.3 2420.65   214.7  2421.8
#Mann= 4 ,-1,0
       0     .08       0      10      .1       0    94.7    .045       0
   106.7      .1       0
Bank Sta=94.7,106.7
XS Rating Curve= 0 ,0
Exp/Cntr(USF)=0,0
Exp/Cntr=0.3,0.1

Type RM Length L Ch R = 1 ,2468    ,97.9,97,97.1
XS GIS Cut Line= 2
2243277.51081095639065.9672082172243705.31190851639229.437433875
#Sta/Elev= 30
       0 2454.13    11.4 2449.75    32.8 2439.68    45.7 2431.95    57.2 2426.19
    92.8 2411.05   114.2 2405.83   131.6 2403.25     157 2394.06   169.9 2388.36
   204.1 2379.35   208.4 2378.72   215.2 2379.37   218.3 2380.22   229.8 2386.15
   238.4  2384.4   251.2 2385.62   258.6 2384.53   268.3 2388.39   276.9 2389.43
   300.4  2400.8   310.9 2406.93   315.4 2408.36   328.3 2410.05   345.4 2409.39
     384 2411.45   409.6 2416.65   443.9 2420.38   448.2 2421.47     458 2427.08
#Mann= 3 ,-1,0
       0      .1       0   204.1    .045       0   215.2      .1       0
Bank Sta=204.1,215.2
XS Rating Curve= 0 ,0
Exp/Cntr(USF)=0,0
Exp/Cntr=0.3,0.1

Type RM Length L Ch R = 1 ,2371    ,184.9,183.5,182.3
XS GIS Cut Line= 2
2243265.85675057639172.3205878942243668.35085614639305.880944246
#Sta/Elev= 30
       0 2440.25    27.7 2426.96    34.2 2421.83    40.8 2415.14    44.6 2413.76
    56.3 2411.54    69.9 2406.02    86.7 2397.82    95.2 2397.28   103.8 2393.17
   116.2 2391.32   137.3 2390.91   141.5 2389.97   145.7 2388.42   149.9 2385.71
   158.4 2375.85  160.62 2374.88   163.9 2374.11   173.4 2374.88   179.5 2377.42
   183.7 2378.09   204.7 2378.14   230.4 2380.65   242.7 2385.16   263.7 2389.27
   284.1 2400.55   293.2 2403.06   390.2 2408.84   401.2 2411.15   424.1  2419.8
#Mann= 3 ,-1,0
       0      .1       0  160.62    .045       0   173.4      .1       0
Bank Sta=160.62,173.4
XS Rating Curve= 0 ,0
Exp/Cntr(USF)=0,0
Exp/Cntr=0.3,0.1

Type RM Length L Ch R = 1 ,2187    ,121.8,122.8,124.1
XS GIS Cut Line= 4
 2243214.7099371639345.190488513 2243303.3811674639395.005786436
2243468.76795651639412.9392936892243596.29511919639423.898659232
#Sta/Elev= 30
       0 2431.07     1.7 2429.78    10.9 2428.77    15.4 2427.21    33.8 2413.63
    61.3 2400.23    88.9  2388.2   101.7 2385.19   122.6 2382.96   126.6  2381.2
   130.7 2380.42   142.7 2380.09   150.8 2376.99   162.9 2374.15     179 2373.07
     183  2371.2     187 2368.22     191 2367.47  197.18  2368.2   211.1 2370.39
   231.3 2370.83   239.3 2371.89   259.4 2385.56   267.1 2388.85   275.5    2391
   307.6 2392.92   331.7 2395.25   367.8 2396.62   383.9 2399.27   396.1 2399.56
#Mann= 3 ,-1,0
       0      .1       0     187    .045       0  197.18      .1       0
#XS Ineff= 2 , 0
                          211.06         2376.32
Permanent Ineff=
       F       F
Bank Sta=187,197.18
XS Rating Curve= 0 ,0
Exp/Cntr(USF)=0,0
Exp/Cntr=0.3,0.1

Type RM Length L Ch R = 1 ,2064    ,242.1,237.1,233.4
XS GIS Cut Line= 3
2243162.24032499639455.6510746852243383.27908569639528.892232504
2243639.00587518639523.921099169
#Sta/Elev= 30
       0 2449.94    10.5  2443.5    18.9  2436.5    27.3 2435.57    31.5 2433.57
    48.4 2420.48    75.5 2402.35      99 2394.35   126.2 2383.38   135.7 2380.81
   145.3 2376.01   166.4 2369.95   183.2 2366.77   195.9 2358.39   200.1 2357.52
  203.83 2358.38   216.9 2362.01   242.2 2361.49   269.8 2363.67   281.8 2362.04
   309.8 2364.58   317.8  2366.8   325.8 2370.77   345.8 2384.13   357.8 2387.89
   365.8 2389.52   377.8 2389.77   425.8 2395.69   437.8 2396.25   488.6 2408.63
#Mann= 3 ,-1,0
       0      .1       0   195.9    .045       0  203.83      .1       0
#XS Ineff= 2 , 0
                          228.15         2367.87
Permanent Ineff=
       F       F
Bank Sta=195.9,203.83
XS Rating Curve= 0 ,0
Exp/Cntr(USF)=0,0
Exp/Cntr=0.3,0.1

Type RM Length L Ch R = 1 ,1827    ,261,264.5,266.2
XS GIS Cut Line= 4
2243144.76171085639771.4027229132243280.73484482639766.905695729
2243436.07642268 639706.943112122243590.20408627 639699.79331742
#Sta/Elev= 30
       0 2404.69     3.4 2402.77     7.4 2401.52    15.4  2399.9    51.4  2385.5
    67.5 2380.28      84 2375.84   140.8 2362.61     144  2361.5   161.2 2350.79
   178.3 2346.31   182.6 2345.67   192.6 2346.33     204 2348.85   212.6 2349.37
   225.5 2352.38   242.6 2352.25   251.4 2353.85   257.8 2357.11   276.9 2370.36
   285.2 2372.71   306.7 2376.28   322.7 2376.88   359.6 2379.98   390.8  2384.7
   402.8 2388.12   422.6 2391.03   430.8  2393.9   442.8 2394.62   456.9 2397.82
#Mann= 3 ,-1,0
       0      .1       0   178.3    .045       0   192.6      .1       0
Bank Sta=178.3,192.6
XS Rating Curve= 0 ,0
Exp/Cntr(USF)=0,0
Exp/Cntr=0.3,0.1

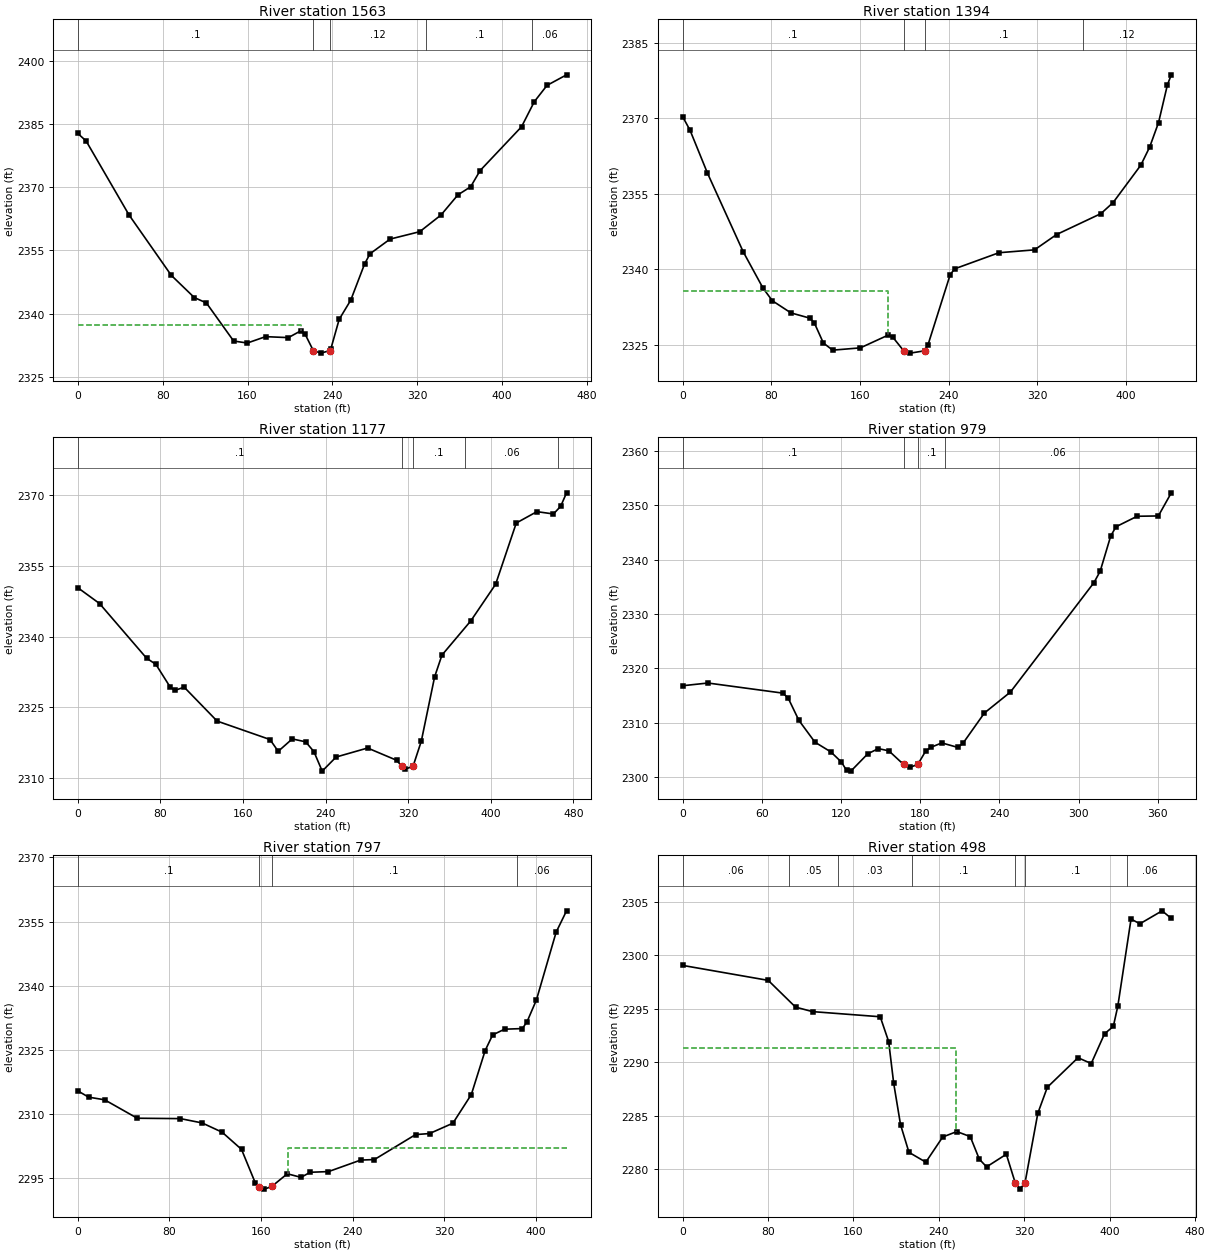
Type RM Length L Ch R = 1 ,1563    ,169.5,169.4,166.7
XS GIS Cut Line= 3
2243147.20961525639932.071657772 2243332.2548849640003.931358494
2243594.52247234640004.481753744
#Sta/Elev= 30
       0 2382.74     7.8 2380.96    48.2 2363.43    88.1 2349.08   109.8 2343.81
   121.2 2342.53   146.9 2333.49   159.8 2333.02     177 2334.53   198.5  2334.3
   210.4 2335.94   214.4 2335.06  222.05  2331.2   229.2 2330.62   237.3  2331.2
   238.4 2331.49   246.4 2338.63   257.3 2343.18   270.4  2351.8   275.5  2354.2
   294.4 2357.68   322.4 2359.44   342.4 2363.39   358.4 2368.18   370.4  2370.1
   379.3 2373.94   418.4 2384.35   430.4 2390.29   442.4 2394.16   460.8 2396.66
#Mann= 5 ,-1,0
       0      .1       0  222.05    .045       0   237.3     .12       0
  328.51      .1       0  428.51     .06       0
#XS Ineff= 2 , 0
          210.09 2337.38
Permanent Ineff=
       F       F
Bank Sta=222.05,237.3
XS Rating Curve= 0 ,0
Exp/Cntr(USF)=0,0
Exp/Cntr=0.3,0.1

Type RM Length L Ch R = 1 ,1394    ,216.5,216.3,212.1
XS GIS Cut Line= 3
2243106.71043827640098.2662765352243279.95614938640151.314381873
2243539.65306932640147.346213112
#Sta/Elev= 30
       0 2370.36     6.7 2367.65    22.4 2359.13    54.7 2343.45    72.6 2336.21
      81 2333.71    97.7  2331.3   114.5 2330.27   118.7 2329.38     127 2325.31
   135.4 2323.88   160.4 2324.34   185.4 2326.87   189.4 2326.53   199.52323.748
   205.4 2323.29  218.28 2323.75   221.4 2324.94   241.4 2338.89   245.4 2340.06
   285.4 2343.27   317.5 2343.84   337.4 2346.89   377.4 2351.05   388.4 2353.25
   413.4 2360.69   421.4  2364.3   429.4 2369.17   437.4 2376.68   440.9 2378.67
#Mann= 4 ,-1,0
       0      .1       0   199.5    .045       0  218.28      .1       0
  361.19     .12       0
#XS Ineff= 2 , 0
          185.13  2335.6
Permanent Ineff=
       F       F
Bank Sta=199.5,218.28
XS Rating Curve= 0 ,0
Exp/Cntr(USF)=0,0
Exp/Cntr=0.3,0.1

Type RM Length L Ch R = 1 ,1177    ,199.4,198,198.8
XS GIS Cut Line= 3
2243113.76989107640223.1534916182243302.72359379640326.159672128
2243560.87802728640330.283256989
#Sta/Elev= 30
       0 2350.38      21 2347.03    66.5 2335.46    75.6 2334.13    89.3 2329.37
    93.9 2328.61     103  2329.3   134.9 2322.11   186.1  2318.2   194.1  2315.7
   207.7 2318.33   220.7 2317.71   228.7 2315.62   236.7  2311.5   250.2 2314.49
   280.7  2316.4   308.7 2313.81  313.87 2312.53   316.7  2311.9   324.7 2312.52
   332.7 2317.85   345.6 2331.49   352.7  2336.1   380.7 2343.37   404.7 2351.12
   424.7  2364.1   444.7 2366.51   460.7 2366.02   467.7 2367.64   473.4  2370.5
#Mann= 5 ,-1,0
       0      .1       0  313.87    .045       0   324.7      .1       0
  375.21     .06       0  465.21      .1       0
Bank Sta=313.87,324.7
XS Rating Curve= 0 ,0
Exp/Cntr(USF)=0,0
Exp/Cntr=0.3,0.1

Type RM Length L Ch R = 1 ,979     ,180,182.7,179.9
XS GIS Cut Line= 3
 2243161.2906131640484.6866237252243258.95932861640501.364029405
2243530.02447679640491.898700364
#Sta/Elev= 30
       0 2316.79    19.2 2317.29      76 2315.43      80 2314.52    88.1 2310.43
   100.3 2306.41   112.3 2304.63   120.3 2302.77   124.3 2301.21   127.5 2301.09
   140.3 2304.27   148.3 2305.23   156.3 2304.82  167.42 2302.32   172.3 2301.79
  178.24 2302.33   184.3 2304.82   188.4 2305.49   196.4 2306.28   208.4 2305.46
   212.4 2306.19   228.7 2311.78   248.4 2315.63   311.7 2335.75   316.4 2337.84
   324.4 2344.32   328.4 2346.02   344.4 2347.95   360.5 2348.01   370.3 2352.26
#Mann= 4 ,-1,0
       0      .1       0  167.42    .045       0  178.24      .1       0
  199.08     .06       0
Bank Sta=167.42,178.24
XS Rating Curve= 0 ,0
Exp/Cntr(USF)=0,0
Exp/Cntr=0.3,0.1

Type RM Length L Ch R = 1 ,797     ,296.7,298.9,299.6
XS GIS Cut Line= 4
2243105.05722938 640549.83262687  2243202.940408640635.060870099
2243366.53282829640631.2983127342243498.24419797640653.666097415
#Sta/Elev= 30
       0 2315.43     9.4 2313.97    23.4 2313.35    51.9 2309.04    89.6 2308.95
   108.6 2307.94   126.1 2305.77     143 2301.76     155 2293.95  158.12 2293.08
     163 2292.47   169.42293.087     183 2296.06     195 2295.22     203 2296.41
     219 2296.57   247.1 2299.26   259.1 2299.38   295.1 2305.22   307.3 2305.46
   327.7 2307.88   343.8 2314.58   355.9 2324.87   362.4 2328.51   372.8 2329.85
   388.4    2330   392.5 2331.61   400.7 2336.71   417.9 2352.53     427 2357.52
#Mann= 4 ,-1,0
       0      .1       0  158.12    .045       0   169.4      .1       0
  383.42     .06       0
#XS Ineff= 2 , 0
                             184         2302.05
Permanent Ineff=
       F       F
Bank Sta=158.12,169.4
XS Rating Curve= 0 ,0
Exp/Cntr(USF)=0,0
Exp/Cntr=0.3,0.1

Type RM Length L Ch R = 1 ,498     ,132.9,130.9,126.7
XS GIS Cut Line= 4
2242986.05831187640770.4575459392243098.23239974640862.456438143
2243289.32269175640926.3406401362243396.48296504640896.873101694
#Sta/Elev= 30
       0 2299.04    80.2 2297.64   105.8 2295.14   121.7 2294.72   185.1 2294.24
     193 2291.92   197.7 2288.03   204.1 2284.16     212 2281.57   227.8 2280.65
   243.6    2283   256.8 2283.51   269.4 2283.04   277.9 2280.93   284.7 2280.21
   303.2 2281.39   311.6  2278.7   315.8 2278.13  320.64 2278.69   332.7 2285.22
   341.6 2287.65   370.3 2290.41   382.7 2289.87   395.2 2292.65   403.4 2293.34
   407.6 2295.22     420 2303.37   428.3 2302.93   449.1 2304.14   457.7 2303.43
#Mann= 7 ,-1,0
       0     .06       0     100     .05       0  145.08     .03       0
  215.08      .1       0   311.6    .045       0  320.64      .1       0
  416.56     .06       0
#XS Ineff= 2 , 0
          256.08 2291.32
Permanent Ineff=
       F       F
Bank Sta=311.6,320.64
XS Rating Curve= 0 ,0
Exp/Cntr(USF)=0,0
Exp/Cntr=0.3,0.1

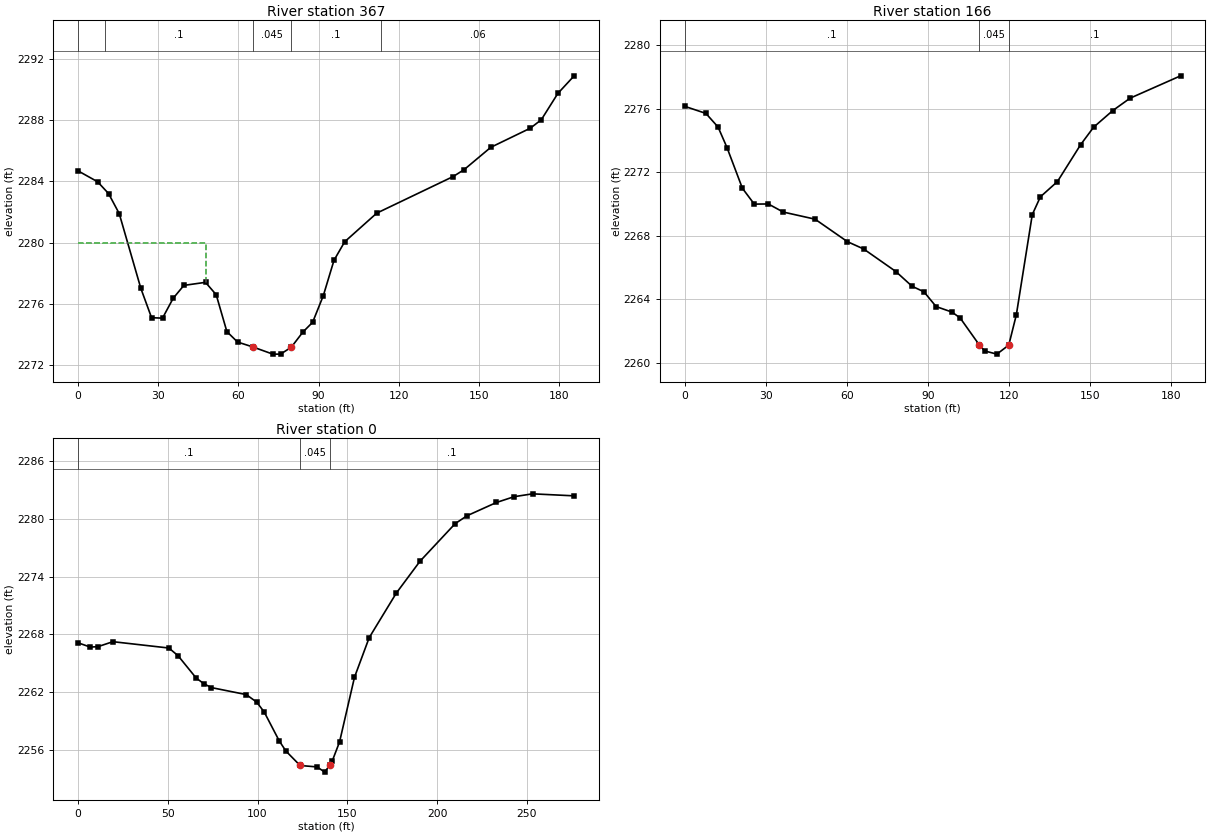
Type RM Length L Ch R = 1 ,367     ,196.7,200.5,204
XS GIS Cut Line= 4
 2243148.9026326641018.3141343372243191.73586984641024.254510304
2243272.90655722 641018.961825582243332.11869293641003.648555498
#Sta/Elev= 30
       0 2284.68     7.3 2283.97    11.4  2283.2    15.4 2281.89    23.5    2277
    27.5 2275.09    31.6 2275.06    35.6 2276.36    39.6  2277.2    47.7  2277.4
    51.7 2276.59    55.7 2274.18    59.7  2273.5    65.4 2273.18    72.9 2272.71
    75.8 2272.71    79.8 2273.16    84.2 2274.16    87.8 2274.79    91.8 2276.53
    95.8 2278.84    99.8 2280.05   111.8 2281.92   140.4 2284.31   144.5 2284.76
   154.5 2286.22   169.3 2287.47   173.4 2288.02   179.6 2289.74   185.7 2290.89
#Mann= 5 ,-1,0
       0     .03       0      10      .1       0    65.4    .045       0
    79.8      .1       0  113.24     .06       0
#XS Ineff= 2 , 0
              48    2280
Permanent Ineff=
       F       F
Bank Sta=65.4,79.8
XS Rating Curve= 0 ,0
Exp/Cntr(USF)=0,0
Exp/Cntr=0.3,0.1

Type RM Length L Ch R = 1 ,166     ,165.2,166.3,164.6
XS GIS Cut Line= 3
2243045.13050645641147.1641586612243188.80431695641220.073256522
2243208.96153812641210.209084458
#Sta/Elev= 30
       0 2276.16     7.9 2275.71    12.4 2274.85    15.7 2273.56    21.4 2270.99
    25.8 2269.99      31    2270    36.5 2269.49    48.3 2269.04    60.3 2267.62
    66.3 2267.16    78.2 2265.74    84.2 2264.81    88.6 2264.46    93.1 2263.53
      99 2263.18     102 2262.81  109.13  2261.1   111.1 2260.73   115.6 2260.53
     120  2261.1   122.8 2263.01   128.7 2269.33   131.7 2270.45     138 2271.41
   146.6 2273.74   151.4 2274.84   158.5 2275.89   164.9 2276.67   183.6 2278.08
#Mann= 3 ,-1,0
       0      .1       0  109.13    .045       0     120      .1       0
Bank Sta=109.13,120
XS Rating Curve= 0 ,0
Exp/Cntr(USF)=0,0
Exp/Cntr=0.3,0.1

Type RM Length L Ch R = 1 ,0       ,54.4,53.3,53.3
XS GIS Cut Line= 3
2243001.71694375641317.2800783722243132.52444285641360.596660042
2243266.63882344641395.469479006
#Sta/Elev= 30
       0 2267.11     6.8 2266.67      11 2266.71    19.4 2267.23    50.6 2266.57
    55.7 2265.77    65.8 2263.45      70 2262.87    74.2 2262.46    93.7 2261.73
    99.5 2260.95   103.7 2259.92   112.1 2256.91   115.8 2255.86   123.7 2254.36
   133.2 2254.21   137.4 2253.67   140.1 2254.36   141.6 2254.82   145.7 2256.82
     154 2263.53   162.2 2267.65   177.3 2272.28   190.5 2275.59   210.1  2279.5
   216.7 2280.32   233.1  2281.7   242.9  2282.3   253.2  2282.6   276.4 2282.39
#Mann= 3 ,-1,0
       0      .1       0   123.7    .045       0   140.1      .1       0
Bank Sta=123.7,140.1
XS Rating Curve= 0 ,0
Exp/Cntr=0.3,0.1
LCMann Table=0

Chan Stop Cuts=-1
Use User Specified Reach Order=0
Composite Channel Slope=5